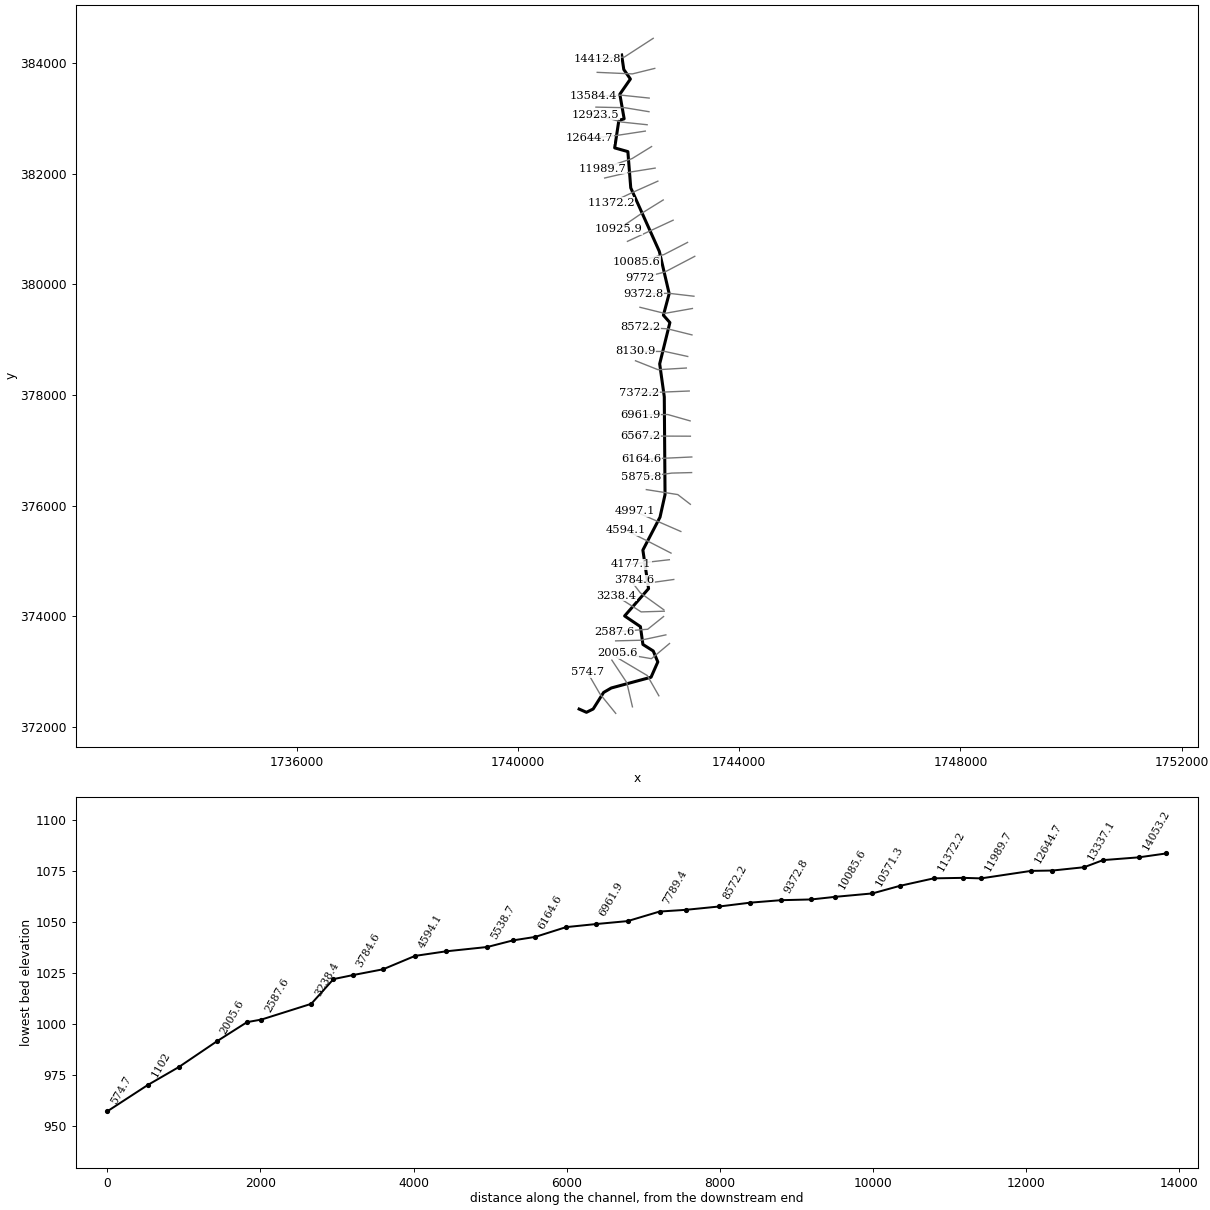
--- MdRn.prj (project) ---

Proj Title=MdRn
Current Plan=p01
Geom File=g01
Flow File=f01
Plan File=p01
DSS Export Rating Curves=0
DSS Export Rating Curve Sorted=0
DSS Export Volume Flow Curves=0
DXF OffsetX=0
DXF OffsetY=0
DXF ScaleX=0
DXF ScaleY=0

--- MdRn.p01 (plan) ---

Plan Title=Floodplain
Program Version=4.00
Geom File=g01
Flow File=f01
K Sum by GR=0
Std Step Tol=0.01
Critical Tol=0.01
Num of Std Step Trials=20
Max Error Tol=0.3
Flow Tol Ratio=0.001
Split Flow NTrial=30
Split Flow Tol=0.02
Split Flow Ratio=0.02
Log Output Level=0
Friction Slope Method=1
Unsteady Friction Slope Method=2
Unsteady Bridges Friction Slope Method=1
Global Log Level=0
CheckData=False
Run HTab=0
Run UNet=0
Run PostProcess=0
UNET Theta=0
UNET Theta Warmup=0
UNET ZTol=0
UNET ZSATol=0
UNET MxIter=0
UNET MaxInSteps=0
UNET DtIC=0
UNET DtMin=0
UNET MaxCRTS=0
UNET WFStab=0
UNET SFStab=0
UNET WFX=0
UNET SFX=0
UNET DSS MLevel=0
UNET DZMax Abort=0
UNET Convert EG Bridges=0
UNET Use Existing IB Tables=0
UNET Froude Limit=0
UNET Froude Power=0
Write IC File=0
Echo Input=False
Echo Output=False
Write Detailed=0

--- MdRn.f01 (steady flow) ---

Flow Title=NFF Regression Equation
Program Version=4.00
Number of Profiles=1
Profile Names=P100yr
River Rch & RM=MdRn,Main      ,14412.8
     789
River Rch & RM=MdRn,Main      ,13337.1
     867
River Rch & RM=MdRn,Main      ,11989.7
     926
River Rch & RM=MdRn,Main      ,9772
    1010
River Rch & RM=MdRn,Main      ,7372.2
    1096
River Rch & RM=MdRn,Main      ,3528.6
    1196
River Rch & RM=MdRn,Main      ,3238.4
    1435
Boundary for River Rch & Prof#=MdRn,Main      ,1
Up Type=0
Dn Type=3
Dn Slope=0.023314

--- MdRn.g01 (geometry) ---

Geom Title=USGS 3m DEM
Program Version=4.00

River Reach=MdRn     ,Main
Reach XY= 30
     1741876.079      384144.758     1741915.141      383882.171
     1742034.483      383709.842     1741843.527      383435.123
     1741921.652      382990.244     1741826.165      382962.032
     1741750.211      382465.071     1741988.926      382397.796
     1742041.009      381742.414     1742557.502      380594.411
     1742735.454      379830.522     1742631.287      379439.897
     1742748.475      379307.519     1742564.013      378560.991
     1742647.262      377964.368     1742660.718      376197.541
     1742570.057      375790.017     1742260.104      375194.592
     1742362.850      374497.994     1741930.186      374004.061
     1742215.543      373811.042     1742260.922      373488.699
     1742447.686      373370.619     1742530.123      373172.837
     1742408.085      372896.457     1741689.287      372701.808
     1741550.633      372621.451     1741361.558      372322.084
     1741240.236      372262.211     1741107.652      372320.890

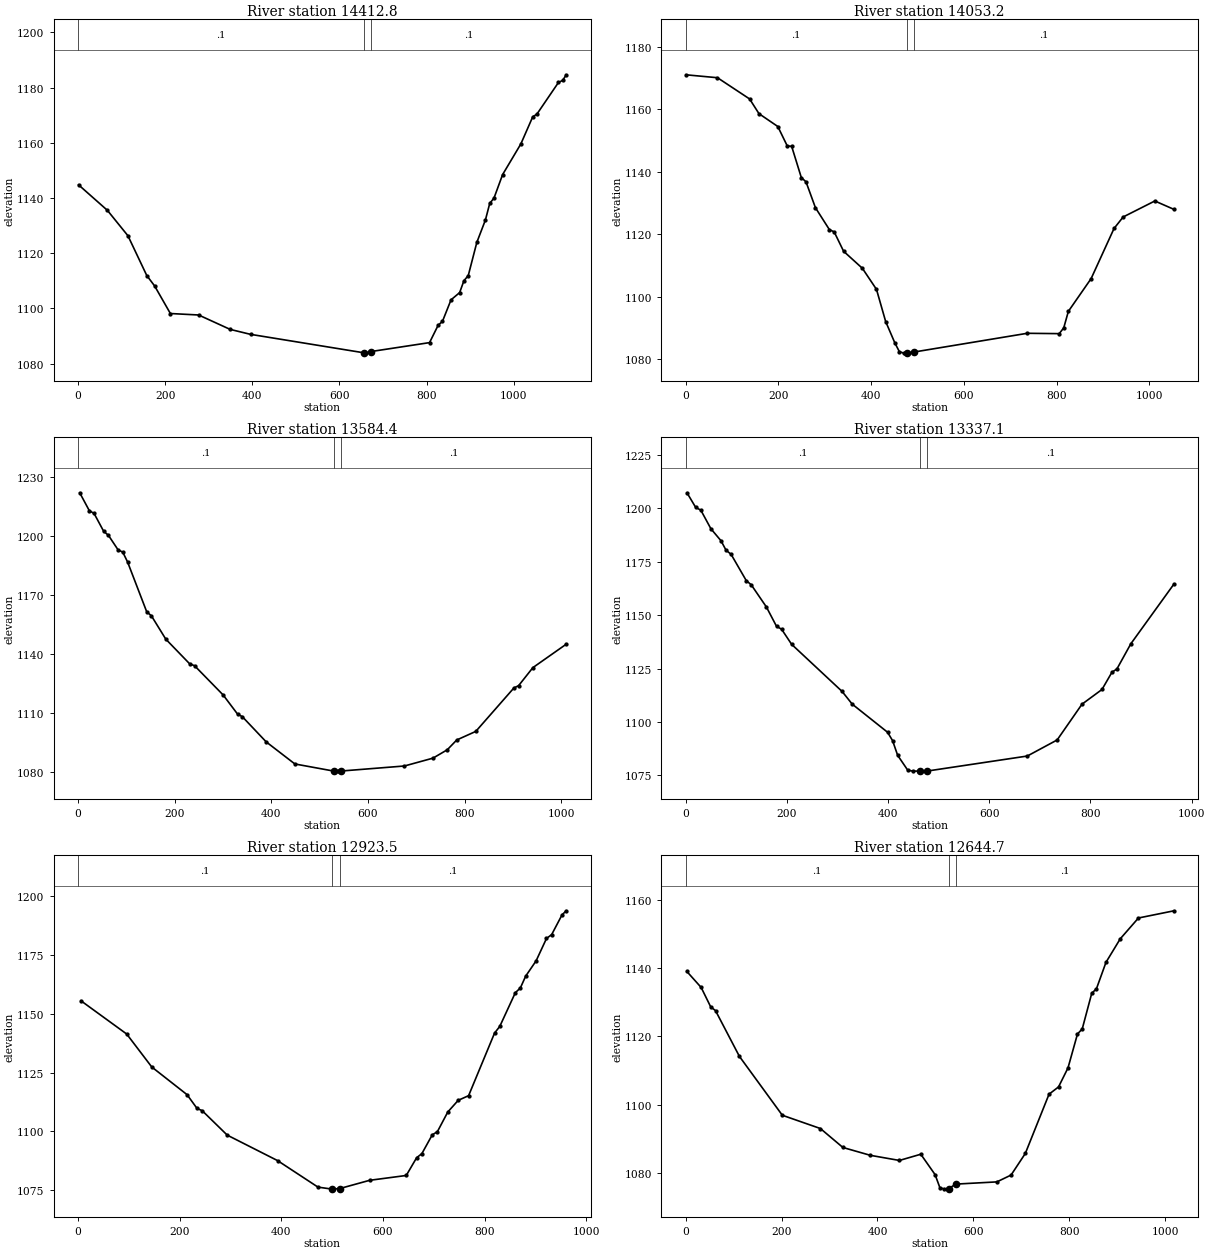
Type RM Length L Ch R = 1 ,14412.8,364.4,359.6,352.9
XS GIS Cut Line= 3
     1742446.873      384445.466     1741925.190      384106.993
     1741427.830      384074.980
#Sta/Elev= 30
     1.4 1144.78    67.5 1135.55   114.7 1126.33   157.9 1111.93   176.0 1108.13
   212.1 1098.15   276.9 1097.62   349.3 1092.40   396.2 1090.60   656.9 1083.90
   658.9 1083.80   671.9 1084.36   806.8 1087.61   826.6 1093.92   836.4 1095.30
   856.1 1103.11   875.9 1105.74   885.7 1110.05   895.6 1111.88   915.3 1123.93
   935.0 1132.04   944.9 1138.05   954.7 1139.99   974.5 1148.51  1016.3 1159.60
  1043.5 1169.41  1053.3 1170.44  1102.6 1181.88  1112.5 1182.66  1120.3 1184.65
#Mann= 3 , 0 , 0
       0     0.1       0   656.9   0.045       0   671.9     0.1       0
Bank Sta=   656.9,   671.9
Exp/Cntr=0.3,0.1

Type RM Length L Ch R = 1 ,14053.2,465,468.8,471.6
XS GIS Cut Line= 3
     1742474.820      383902.046     1742071.137      383802.678
     1741434.560      383830.625
#Sta/Elev= 30
     1.4 1171.00    68.7 1170.07   138.0 1163.27   158.2 1158.56   198.8 1154.45
   219.1 1148.25   228.7 1148.09   249.5 1138.10   259.6 1136.74   279.9 1128.46
   310.0 1121.44   320.4 1120.70   340.7 1114.50   381.2 1109.04   411.6 1102.30
   431.4 1092.00   451.1 1085.19   461.0 1082.33   470.8 1081.88   476.7 1081.93
   491.7 1082.21   736.7 1088.23   805.7 1088.12   815.5 1089.98   825.4 1095.25
   874.6 1105.77   923.9 1121.79   943.6 1125.48  1011.9 1130.60  1052.9 1127.93
#Mann= 3 , 0 , 0
       0     0.1       0   476.7   0.045       0   491.7     0.1       0
Bank Sta=   476.7,   491.7
Exp/Cntr=0.3,0.1

Type RM Length L Ch R = 1 ,13584.4,252.6,247.4,243.6
XS GIS Cut Line= 3
     1742374.078      383365.616     1741875.506      383417.626
     1741366.244      383402.100
#Sta/Elev= 30
     3.7 1221.93    23.5 1212.87    33.4 1211.44    53.2 1202.39    63.1 1200.32
    82.9 1193.00    92.8 1191.77   102.7 1186.79   142.2 1161.54   152.1 1159.39
   181.8 1147.57   231.3 1135.00   241.2 1134.10   300.5 1119.20   330.2 1109.52
   340.1 1108.19   389.6 1095.36   448.9 1084.15   529.6 1080.52   537.8 1080.51
   544.6 1080.56   675.6 1083.12   734.7 1087.11   764.2 1091.35   783.9 1096.34
   823.3 1100.70   902.1 1122.76   911.9 1123.95   941.4 1133.10  1010.3 1144.99
#Mann= 3 , 0 , 0
       0     0.1       0   529.6   0.045       0   544.6     0.1       0
Bank Sta=   529.6,   544.6
Exp/Cntr=0.3,0.1

Type RM Length L Ch R = 1 ,13337.1,386.2,413.6,422.7
XS GIS Cut Line= 3
     1742370.435      383119.240     1741932.523      383191.540
     1741411.710      383202.211
#Sta/Elev= 30
     2.7 1207.21    20.0 1200.35    30.0 1199.12    49.9 1190.42    69.9 1184.79
    79.9 1180.35    89.8 1178.46   119.8 1166.16   129.7 1164.18   159.6 1153.82
   179.6 1144.78   189.6 1143.42   209.5 1136.34   309.2 1114.31   329.2 1108.37
   399.0 1095.23   409.0 1091.29   419.0 1084.42   438.9 1077.48   448.8 1077.03
   462.4 1077.05   477.4 1077.07   675.2 1084.09   734.2 1091.61   783.3 1108.34
   822.8 1115.22   842.5 1123.29   852.3 1124.82   879.8 1136.59   964.8 1164.47
#Mann= 3 , 0 , 0
       0     0.1       0   462.4   0.045       0   477.4     0.1       0
Bank Sta=   462.4,   477.4
Exp/Cntr=0.3,0.1

Type RM Length L Ch R = 1 ,12923.5,269,278.8,289.9
XS GIS Cut Line= 3
     1742337.673      382883.464     1741879.190      382931.530
     1741398.285      383065.418
#Sta/Elev= 30
     6.1 1155.47    95.9 1141.36   145.2 1127.34   214.5 1115.59   234.3 1109.70
   244.2 1108.79   293.6 1098.37   392.6 1087.53   472.1 1076.25     500 1075.40
     515 1075.65   573.7 1079.15   645.7 1081.21   666.1 1088.76   676.4 1090.49
   696.8 1098.48   707.0 1099.86   727.4 1108.21   747.9 1113.17   768.3 1115.14
   819.4 1141.78   829.6 1144.59   860.2 1158.93   870.1 1160.96   880.6 1165.99
   901.1 1172.49   921.5 1182.00   931.7 1183.66   952.1 1192.05   960.2 1193.76
#Mann= 3 , 0 , 0
       0     0.1       0     500   0.045       0     515     0.1       0
Bank Sta=     500,     515
Exp/Cntr=0.3,0.1

Type RM Length L Ch R = 1 ,12644.7,642.5,654.9,656.7
XS GIS Cut Line= 3
     1742304.031      382768.627     1741773.032      382687.891
     1741294.823      382638.207
#Sta/Elev= 30
     2.6 1138.98    32.4 1134.30    52.3 1128.61    62.3 1127.52   112.1 1114.12
   201.6 1096.87   281.0 1092.98   327.9 1087.43   385.2 1085.13   445.7 1083.63
   490.3 1085.45   520.1 1079.48   530.1 1075.66   539.6 1075.23   548.2 1075.36
   563.2 1076.70   648.9 1077.35   678.5 1079.35   708.2 1085.67   757.7 1103.04
   777.5 1105.17   797.2 1110.73   817.0 1120.68   826.9 1122.15   846.7 1132.58
   856.6 1133.94   876.4 1141.66   906.1 1148.54   944.1 1154.65  1017.9 1156.75
#Mann= 3 , 0 , 0
       0     0.1       0   548.2   0.045       0   563.2     0.1       0
Bank Sta=   548.2,   563.2
Exp/Cntr=0.3,0.1

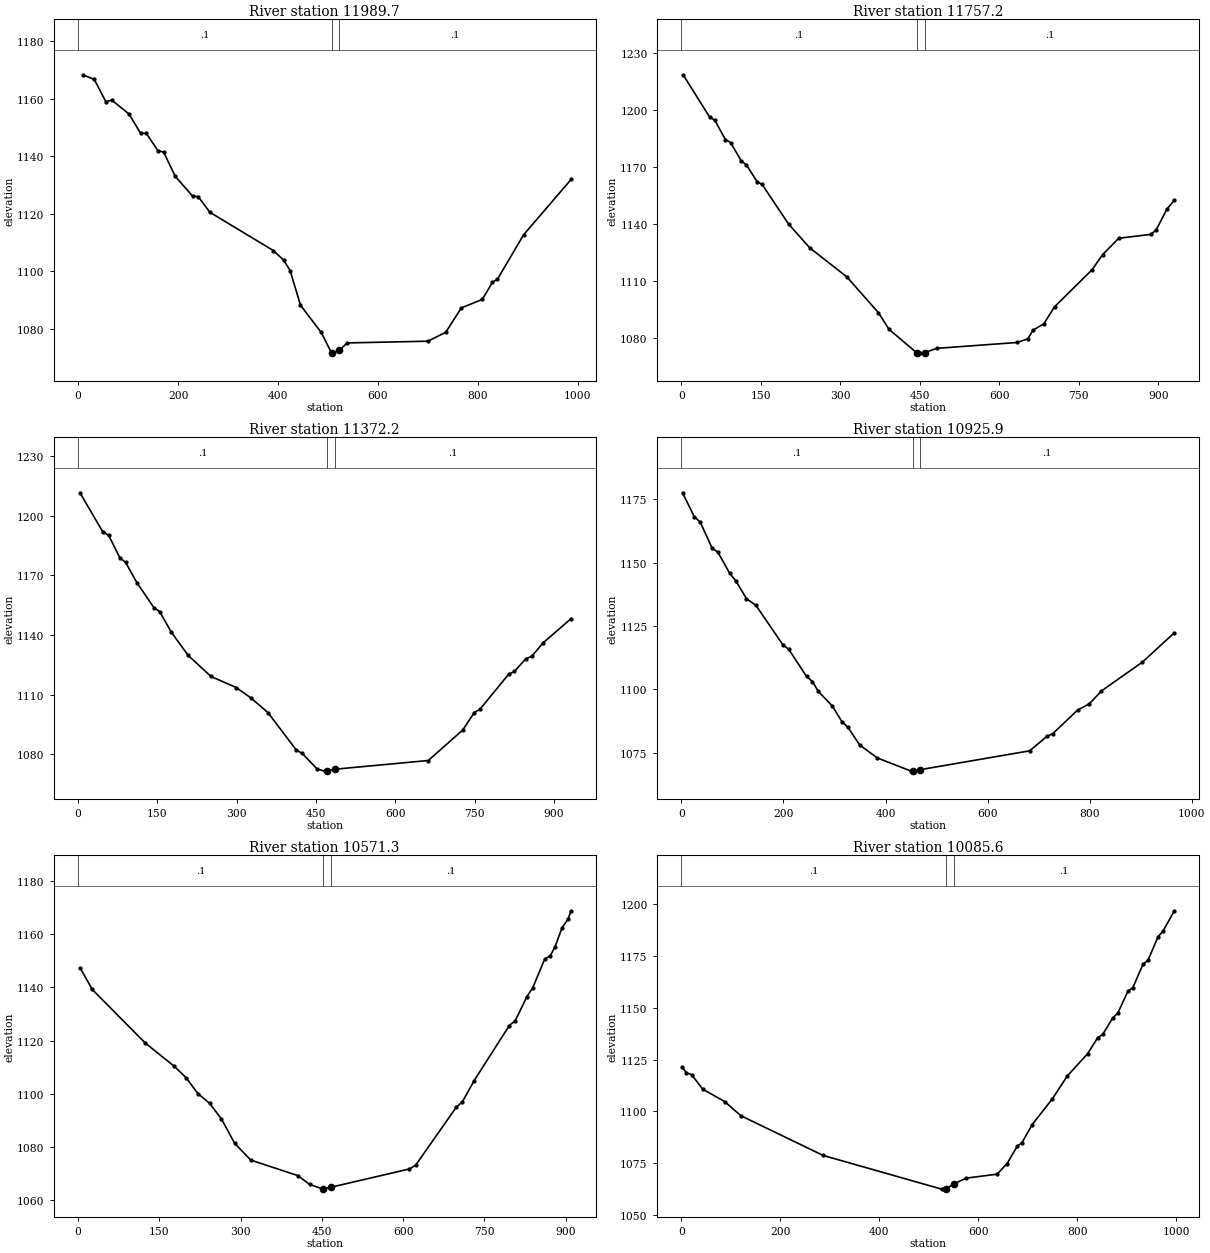
Type RM Length L Ch R = 1 ,11989.7,242.3,232.5,229.8
XS GIS Cut Line= 3
     1742417.529      382489.057     1742064.927      382271.786
     1741522.651      382089.103
#Sta/Elev= 30
     9.2 1168.36    32.3 1166.75    55.4 1159.00    67.0 1159.58   101.6 1154.75
   124.8 1148.05   136.3 1148.01   159.4 1142.00   171.0 1141.49   194.1 1133.09
   228.8 1126.20   240.3 1125.97   263.5 1120.55   390.6 1107.22   411.0 1103.95
   424.1 1100.28   444.9 1088.21   486.4 1078.75   507.2 1071.55   507.3 1071.55
   522.3 1072.50   538.4 1075.10   699.9 1075.70   735.6 1078.80   766.8 1087.29
   808.7 1090.24   829.1 1096.18   839.0 1097.25   891.4 1112.71   986.4 1131.96
#Mann= 3 , 0 , 0
       0     0.1       0   507.3   0.045       0   522.3     0.1       0
Bank Sta=   507.3,   522.3
Exp/Cntr=0.3,0.1

Type RM Length L Ch R = 1 ,11757.2,379,385,389.8
XS GIS Cut Line= 3
     1742481.817      382099.776     1742036.405      382028.906
     1741569.518      381920.627
#Sta/Elev= 30
     3.3 1218.52    53.1 1196.31    63.0 1194.57    83.0 1184.39    92.9 1182.81
   112.9 1173.18   122.8 1171.00   142.8 1162.21   152.3 1160.71   202.5 1139.76
   242.4 1127.25   312.1 1112.05   371.9 1093.11   391.8 1084.34   444.3 1071.94
   451.0 1071.81   459.3 1072.08   481.9 1074.32   634.0 1077.43   653.7 1079.36
   663.8 1083.93   684.0 1087.27   704.2 1096.22   774.9 1115.72   795.1 1123.77
   825.4 1132.36   886.0 1134.40   896.1 1136.79   916.3 1147.71   930.3 1152.38
#Mann= 3 , 0 , 0
       0     0.1       0   444.3   0.045       0   459.3     0.1       0
Bank Sta=   444.3,   459.3
Exp/Cntr=0.3,0.1

Type RM Length L Ch R = 1 ,11372.2,441.4,446.3,450.5
XS GIS Cut Line= 3
     1742530.897      381863.988     1742100.048      381671.622
     1741682.922      381476.584
#Sta/Elev= 30
     3.4 1211.45    46.5 1191.86    57.7 1190.05    78.8 1178.81    89.6 1176.50
   111.2 1166.23   143.5 1153.65   154.2 1151.76   175.8 1141.55   208.1 1129.73
   251.2 1119.15   299.0 1113.58   326.7 1108.35   359.0 1100.98   412.9 1082.05
   423.7 1080.52   452.2 1072.55   466.8 1071.57     471 1071.72     486 1072.54
   662.3 1076.91   727.4 1092.24   749.2 1101.01   760.0 1102.67   814.3 1120.31
   825.2 1121.70   846.9 1128.13   857.8 1129.24   879.5 1136.07   932.3 1148.21
#Mann= 3 , 0 , 0
       0     0.1       0     471   0.045       0     486     0.1       0
Bank Sta=     471,     486
Exp/Cntr=0.3,0.1

Type RM Length L Ch R = 1 ,10925.9,357.9,354.6,351
XS GIS Cut Line= 3
     1742628.075      381523.801     1742251.242      381290.526
     1741819.611      380995.526
#Sta/Elev= 30
     2.2 1177.44    25.4 1167.98    36.9 1165.91    60.1 1155.69    71.6 1154.03
    94.8 1145.68   106.4 1142.85   127.4 1135.78   146.1 1133.09   198.9 1117.60
   210.5 1115.75   245.2 1105.16   256.8 1103.13   268.4 1099.22   295.7 1093.51
   314.7 1087.29   326.2 1085.15   349.4 1078.13   384.1 1073.02   450.3 1067.85
   452.9 1067.91   467.9 1068.42   682.6 1075.85   716.1 1081.50   728.0 1082.64
   776.5 1091.89   799.5 1094.35   823.3 1099.45   903.4 1110.76   966.0 1122.32
#Mann= 3 , 0 , 0
       0     0.1       0   452.9   0.045       0   467.9     0.1       0
Bank Sta=   452.9,   467.9
Exp/Cntr=0.3,0.1

Type RM Length L Ch R = 1 ,10571.3,489.6,485.7,481.7
XS GIS Cut Line= 3
     1742807.157      381157.813     1742394.331      380966.504
     1741981.504      380775.195
#Sta/Elev= 30
     4.2 1147.11    25.9 1139.23   123.5 1119.15   177.8 1110.27   199.4 1106.00
   221.1 1100.07   242.8 1096.40   264.5 1090.54   289.1 1081.33   318.7 1075.08
   405.5 1069.27   427.2 1065.96   452.2 1064.18   452.6 1064.20   467.6 1064.94
   611.6 1071.76   623.1 1073.18   698.3 1095.04   709.2 1096.94   730.9 1104.92
   795.9 1125.63   806.8 1127.43   828.5 1136.54   839.3 1139.88   861.0 1150.50
   871.8 1151.94   880.5 1155.32   893.5 1162.47   904.4 1165.65   910.0 1168.77
#Mann= 3 , 0 , 0
       0     0.1       0   452.6   0.045       0   467.6     0.1       0
Bank Sta=   452.6,   467.6
Exp/Cntr=0.3,0.1

Type RM Length L Ch R = 1 ,10085.6,308.9,313.6,313.4
XS GIS Cut Line= 3
     1743067.924      380756.421     1742639.399      380535.948
     1742141.803      380405.352
#Sta/Elev= 30
     1.4 1121.56     9.9 1118.78    20.9 1117.68    43.1 1110.77    87.3 1104.80
   120.5 1097.90   286.5 1078.77   526.1 1062.50   535.7 1062.68   550.7 1065.07
   575.9 1067.82   638.0 1069.71   658.3 1074.80   678.7 1083.17   688.3 1084.86
   709.2 1093.71   749.9 1106.12   780.4 1117.25   821.1 1127.87   841.5 1135.62
   851.6 1137.19   872.0 1145.20   882.1 1147.51   902.5 1157.97   912.7 1159.83
   933.0 1171.03   943.2 1173.06   963.5 1184.32   973.7 1187.17   996.4 1196.90
#Mann= 3 , 0 , 0
       0     0.1       0   535.7   0.045       0   550.7     0.1       0
Bank Sta=   535.7,   550.7
Exp/Cntr=0.3,0.1

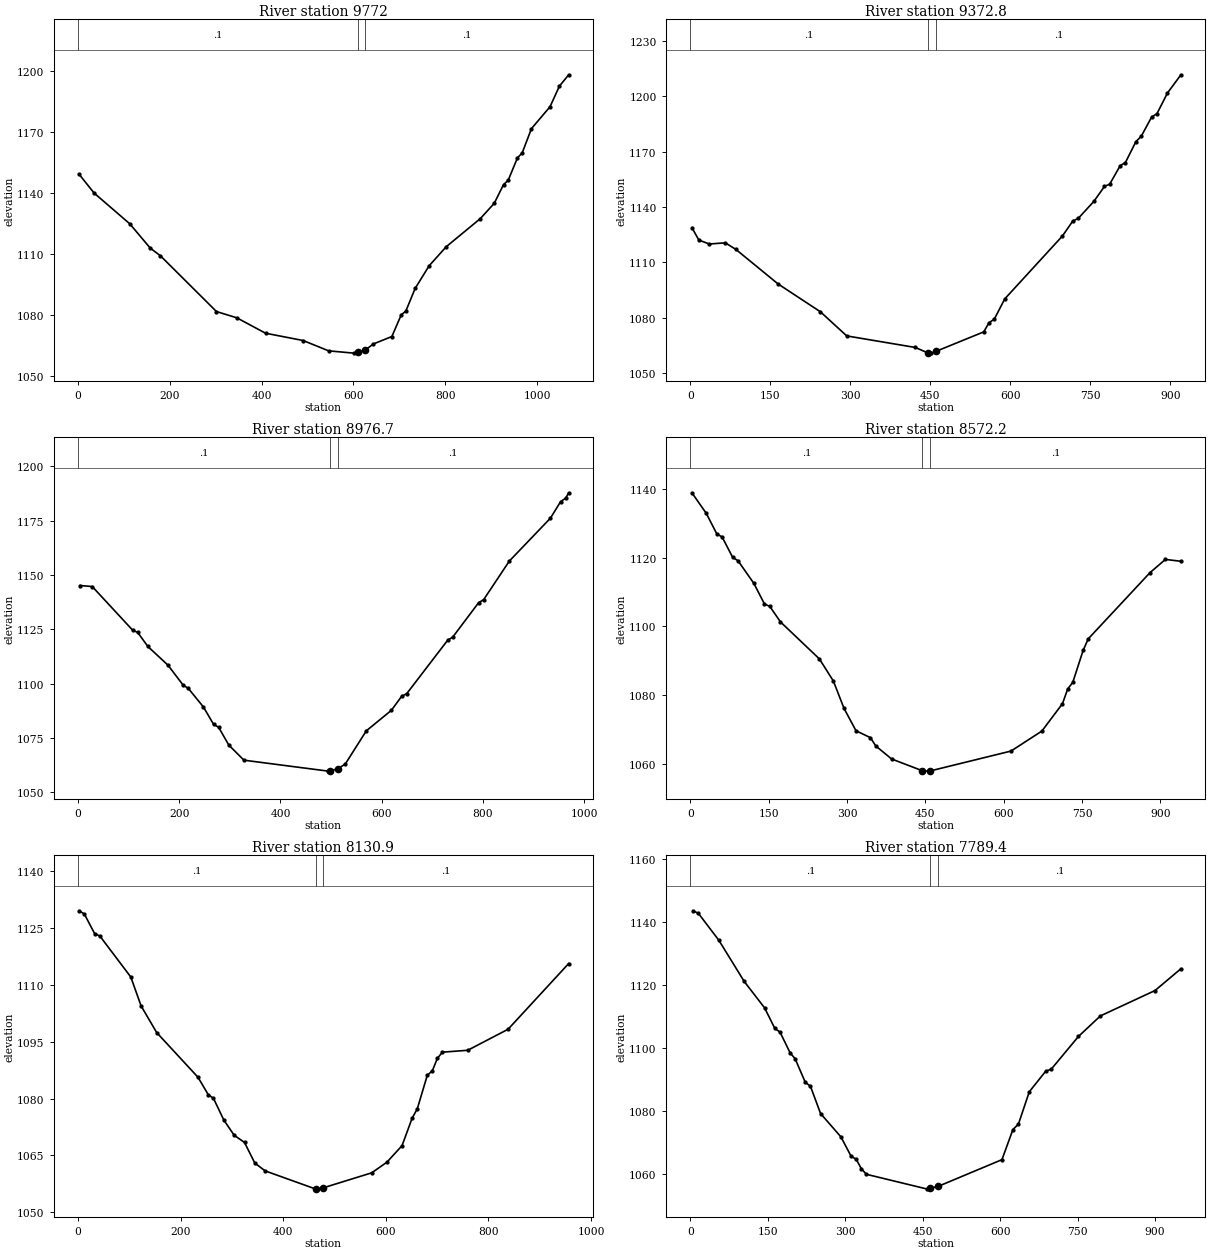
Type RM Length L Ch R = 1 ,9772,413.3,399.2,393.5
XS GIS Cut Line= 3
     1743198.345      380504.896     1742653.410      380219.302
     1742212.726      380110.226
#Sta/Elev= 30
     1.6 1149.24    34.9 1139.83   112.7 1124.72   157.1 1112.84   179.4 1109.03
   301.6 1081.64   346.0 1078.55   408.5 1071.00   490.4 1067.41   546.0 1062.34
   600.7 1061.22     610 1061.58     625 1062.56   643.3 1065.70   683.8 1069.38
   704.1 1079.98   714.2 1081.86   734.5 1092.99   764.9 1104.09   802.2 1113.46
   876.4 1127.25   906.8 1134.77   927.1 1143.97   937.2 1146.09   957.5 1157.14
   967.7 1159.50   987.9 1171.45  1028.5 1182.24  1048.7 1192.28  1069.0 1197.88
#Mann= 3 , 0 , 0
       0     0.1       0     610   0.045       0     625     0.1       0
Bank Sta=     610,     625
Exp/Cntr=0.3,0.1

Type RM Length L Ch R = 1 ,9372.8,385.9,396.1,389.6
XS GIS Cut Line= 3
     1743183.316      379783.576     1742733.516      379836.150
     1742266.427      379830.926
#Sta/Elev= 30
     3.0 1128.88    16.0 1122.15    35.8 1120.01    65.6 1120.66    85.4 1117.10
   164.6 1098.36   243.9 1083.28   293.4 1070.18   422.2 1063.91   446.1 1060.87
   451.9 1060.85   461.1 1061.86   550.3 1072.37   560.2 1077.36   570.0 1079.22
   589.7 1090.25   697.7 1124.31   717.5 1132.55   727.4 1133.86   757.0 1143.19
   776.7 1151.24   786.5 1152.46   806.2 1162.49   816.0 1164.20   835.7 1175.55
   845.6 1178.39   865.2 1188.89   875.1 1190.66   894.8 1201.87   920.0 1211.74
#Mann= 3 , 0 , 0
       0     0.1       0   446.1   0.045       0   461.1     0.1       0
Bank Sta=   446.1,   461.1
Exp/Cntr=0.3,0.1

Type RM Length L Ch R = 1 ,8976.7,406.3,404.5,414.9
XS GIS Cut Line= 3
     1743155.559      379562.018     1742654.370      379472.913
     1742207.366      379583.806
#Sta/Elev= 30
     4.2 1145.14    28.0 1144.68   107.9 1124.57   117.9 1123.54   137.9 1117.08
   177.9 1108.41   207.8 1099.23   217.8 1097.79   247.8 1089.19   267.8 1081.21
   277.8 1079.85   297.8 1071.69   327.8 1064.69   494.3 1059.65   498.6 1059.70
   513.6 1060.82   527.9 1062.85   569.7 1078.22   619.2 1087.65   639.5 1094.12
   649.6 1095.35   730.7 1120.02   740.3 1121.33   791.5 1137.20   801.7 1138.68
   852.4 1156.43   933.5 1176.16   953.7 1183.79   963.9 1185.42   969.6 1187.85
#Mann= 3 , 0 , 0
       0     0.1       0   498.6   0.045       0   513.6     0.1       0
Bank Sta=   498.6,   513.6
Exp/Cntr=0.3,0.1

Type RM Length L Ch R = 1 ,8572.2,434.9,441.3,443.9
XS GIS Cut Line= 3
     1743147.768      379084.531     1742705.886      379194.730
     1742222.020      379218.998
#Sta/Elev= 30
     3.1 1138.91    30.5 1132.95    50.8 1126.92    60.9 1126.04    81.2 1120.08
    91.3 1119.12   121.7 1112.51   142.0 1106.49   152.2 1105.81   172.5 1101.30
   247.1 1090.50   273.9 1084.05   294.2 1076.10   317.2 1069.55   344.9 1067.53
   355.0 1065.13   385.4 1061.32   444.3 1057.89   446.3 1057.78   459.3 1057.84
   614.0 1063.63   673.1 1069.46   712.5 1077.44   722.4 1081.69   732.3 1083.69
   752.0 1092.95   761.8 1096.34   880.0 1115.63   909.6 1119.50   939.2 1118.95
#Mann= 3 , 0 , 0
       0     0.1       0   444.3   0.045       0   459.3     0.1       0
Bank Sta=   444.3,   459.3
Exp/Cntr=0.3,0.1

Type RM Length L Ch R = 1 ,8130.9,339.8,341.5,343.3
XS GIS Cut Line= 3
     1743071.030      378694.531     1742661.136      378784.584
     1742123.926      378787.689
#Sta/Elev= 30
     2.1 1129.58    12.2 1128.75    32.3 1123.56    42.4 1122.94   102.8 1112.11
   123.0 1104.45   153.2 1097.46   233.8 1085.65   253.9 1081.03   264.0 1080.08
   284.2 1074.35   304.3 1070.35   324.5 1068.44   344.6 1063.00   364.8 1060.93
   463.2 1056.15   464.4 1056.12   478.2 1056.47   572.7 1060.43   602.2 1063.24
   631.7 1067.61   651.4 1074.87   661.3 1077.29   680.9 1086.17   690.8 1087.37
   700.6 1090.67   710.5 1092.27   759.7 1092.77   838.4 1098.32   956.5 1115.66
#Mann= 3 , 0 , 0
       0     0.1       0   463.2   0.045       0   478.2     0.1       0
Bank Sta=   463.2,   478.2
Exp/Cntr=0.3,0.1

Type RM Length L Ch R = 1 ,7789.4,417.5,417.2,416.8
XS GIS Cut Line= 3
     1743045.338      378485.837     1742533.820      378455.427
     1742127.032      378616.900
#Sta/Elev= 30
     5.4 1143.65    15.6 1142.87    55.2 1134.32   104.4 1121.23   143.9 1112.83
   163.6 1106.34   173.8 1105.12   193.2 1098.58   203.0 1096.68   222.7 1089.19
   232.6 1087.98   252.3 1079.28   291.7 1071.87   311.4 1065.73   321.3 1064.75
   331.2 1061.79   341.0 1059.99   459.3 1055.28   464.9 1055.55   479.9 1056.15
   603.6 1064.64   624.8 1074.21   635.4 1075.89   656.5 1086.19   688.3 1092.73
   699.0 1093.36   751.8 1103.77   794.2 1110.28   900.0 1118.34   950.1 1125.25
#Mann= 3 , 0 , 0
       0     0.1       0   464.9   0.045       0   479.9     0.1       0
Bank Sta=   464.9,   479.9
Exp/Cntr=0.3,0.1

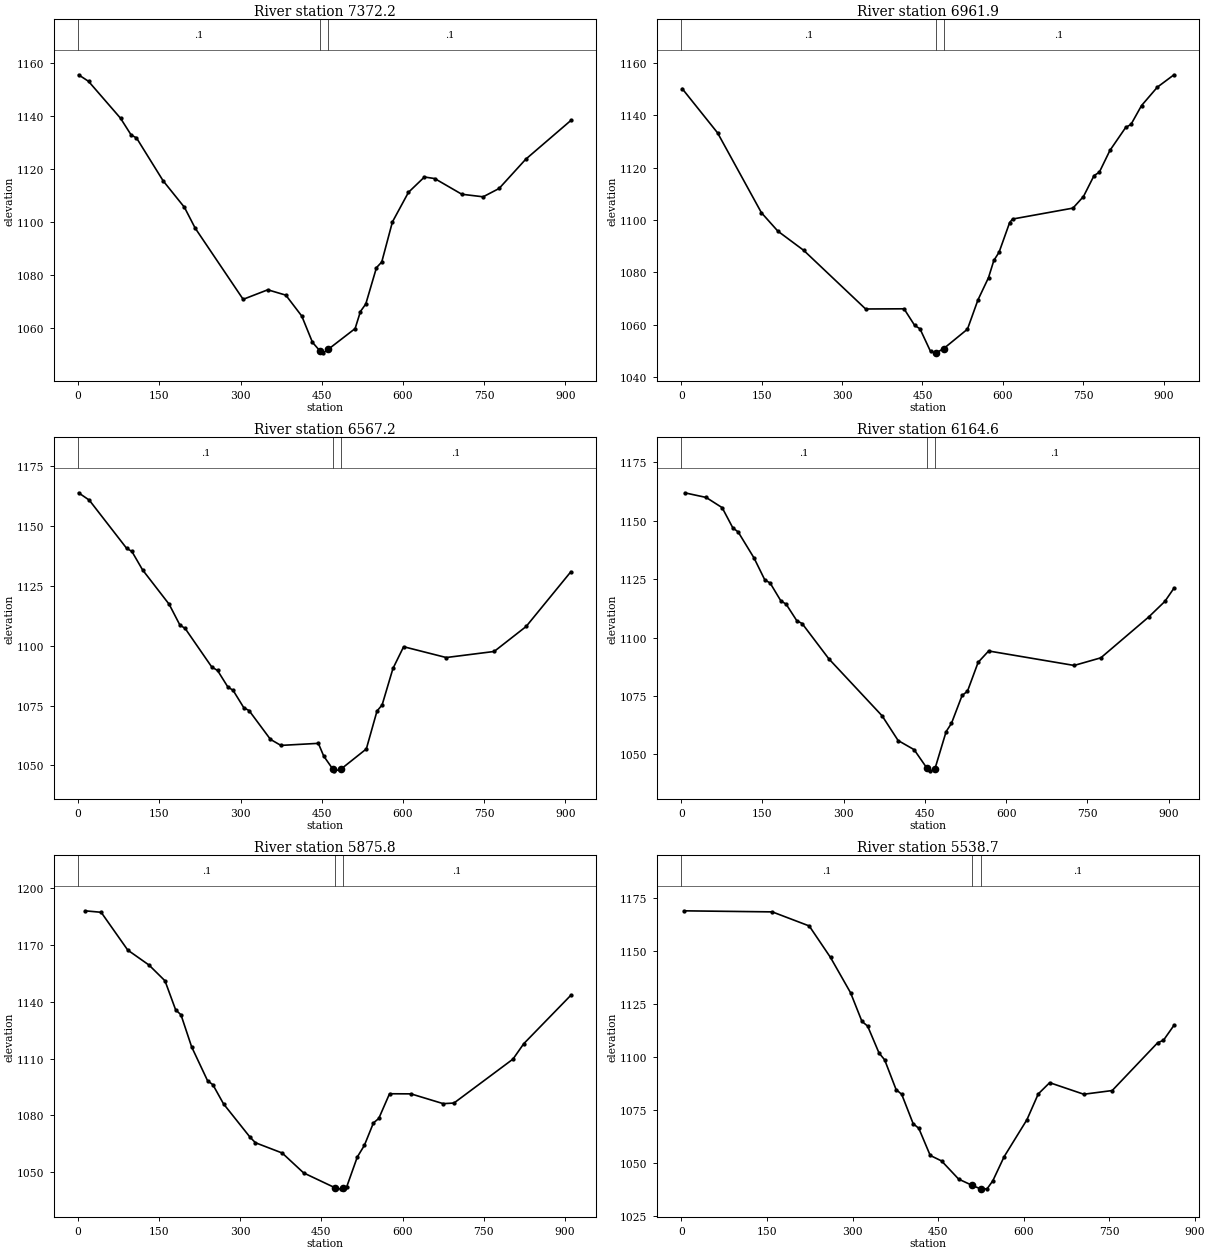
Type RM Length L Ch R = 1 ,7372.2,410.9,410.3,409.6
XS GIS Cut Line= 3
     1743097.887      378070.353     1742643.282      378051.411
     1742188.676      378032.470
#Sta/Elev= 30
     0.8 1155.71    19.1 1153.26    78.2 1139.32    97.9 1132.97   107.7 1131.89
   156.9 1115.68   196.3 1105.65   216.0 1097.84   304.7 1070.92   350.2 1074.52
   383.5 1072.50   413.0 1064.59   432.7 1054.68   447.1 1051.30   451.9 1050.60
   462.1 1052.08   511.5 1059.87   521.3 1066.32   531.2 1069.16   550.9 1082.87
   560.7 1085.03   580.4 1100.16   610.0 1111.33   639.5 1117.12   658.5 1116.53
   708.5 1110.61   747.9 1109.64   777.4 1112.78   826.6 1123.83   910.0 1138.48
#Mann= 3 , 0 , 0
       0     0.1       0   447.1   0.045       0   462.1     0.1       0
Bank Sta=   447.1,   462.1
Exp/Cntr=0.3,0.1

Type RM Length L Ch R = 1 ,6961.9,394.9,394.7,394.5
XS GIS Cut Line= 3
     1743114.503      377530.060     1742710.820      377644.955
     1742211.559      377640.511
#Sta/Elev= 30
     1.8 1150.19    67.8 1133.30   149.6 1102.79   180.3 1095.75   228.4 1088.43
   344.0 1066.02   415.6 1066.09   435.5 1059.73   445.3 1058.47   465.0 1049.82
   474.6 1049.18   474.8 1049.16   489.6 1050.90   533.9 1058.31   553.5 1069.49
   573.2 1078.00   583.1 1084.55   592.9 1087.71   612.6 1099.03   618.0 1100.37
   730.7 1104.55   750.3 1108.98   770.0 1116.96   779.9 1118.27   799.6 1126.57
   829.1 1135.38   838.9 1136.51   858.6 1143.72   888.1 1150.75   919.0 1155.46
#Mann= 3 , 0 , 0
       0     0.1       0   474.6   0.045       0   489.6     0.1       0
Bank Sta=   474.6,   489.6
Exp/Cntr=0.3,0.1

Type RM Length L Ch R = 1 ,6567.2,401.6,402.7,403.8
XS GIS Cut Line= 3
     1743119.024      377253.490     1742664.027      377255.002
     1742209.029      377256.514
#Sta/Elev= 30
     0.8 1163.72    20.5 1160.67    89.4 1140.60    99.2 1139.27   118.9 1131.59
   168.1 1117.21   187.8 1108.60   197.6 1107.14   246.8 1091.05   257.4 1089.63
   276.3 1082.79   286.2 1081.31   305.9 1074.09   315.7 1072.88   355.1 1060.89
   374.4 1058.37   443.6 1059.23   453.5 1053.92   470.2 1048.51   473.1 1047.64
   485.2 1048.45   532.2 1056.89   551.9 1072.69   561.4 1075.27   581.4 1090.47
   601.1 1099.53   679.8 1095.02   768.3 1097.55   827.4 1107.98   910.0 1130.81
#Mann= 3 , 0 , 0
       0     0.1       0   470.2   0.045       0   485.2     0.1       0
Bank Sta=   470.2,   485.2
Exp/Cntr=0.3,0.1

Type RM Length L Ch R = 1 ,6164.6,286.7,288.8,290.8
XS GIS Cut Line= 3
     1743144.473      376877.725     1742689.964      376856.585
     1742235.455      376835.445
#Sta/Elev= 30
     6.6 1161.92    46.0 1159.95    75.6 1155.58    95.3 1146.94   105.1 1145.20
   134.5 1134.04   154.4 1124.66   164.2 1123.34   183.9 1115.74   193.8 1114.27
   213.5 1107.20   223.3 1106.00   272.6 1090.91   371.1 1066.49   400.6 1055.94
   430.2 1052.02   453.4 1044.26   459.7 1042.84   468.4 1043.67   489.3 1059.76
   499.1 1063.26   518.8 1075.22   528.7 1077.02   548.4 1089.39   567.8 1094.25
   725.7 1088.06   775.0 1091.32   863.6 1108.83   893.2 1115.44   910.0 1121.09
#Mann= 3 , 0 , 0
       0     0.1       0   453.4   0.045       0   468.4     0.1       0
Bank Sta=   453.4,   468.4
Exp/Cntr=0.3,0.1

Type RM Length L Ch R = 1 ,5875.8,343.7,337.1,330.5
XS GIS Cut Line= 3
     1743141.030      376595.753     1742782.603      376586.431
     1742234.802      376511.390
#Sta/Elev= 30
    12.7 1187.93    42.5 1187.16    91.7 1167.23   131.1 1159.32   160.6 1151.02
   180.3 1135.71   190.2 1133.08   209.9 1116.18   239.4 1098.30   249.2 1096.22
   268.9 1086.12   318.1 1068.49   328.0 1065.61   377.4 1060.20   417.1 1049.70
   475.8 1041.78   486.6 1041.15   490.8 1041.56   496.5 1042.14   516.4 1058.11
   529.4 1064.19   546.2 1076.07   556.1 1078.42   576.0 1091.45   615.7 1091.39
   675.3 1086.23   695.2 1086.55   804.4 1109.73   824.3 1117.85   911.5 1143.41
#Mann= 3 , 0 , 0
       0     0.1       0   475.8   0.045       0   490.8     0.1       0
Bank Sta=   475.8,   490.8
Exp/Cntr=0.3,0.1

Type RM Length L Ch R = 1 ,5538.7,547.3,541.6,535.9
XS GIS Cut Line= 3
     1743118.656      376022.297     1742890.925      376197.905
     1742322.663      376287.958
#Sta/Elev= 30
     4.5 1169.09   159.5 1168.59   224.2 1161.96   261.5 1147.09   296.6 1130.47
   316.5 1116.98   326.5 1114.75   346.4 1102.09   356.3 1098.84   376.3 1084.85
   386.2 1082.57   406.2 1068.76   416.1 1066.56   436.1 1053.78   456.0 1051.18
   485.9 1042.62   509.9 1039.63   524.9 1037.95   525.7 1037.90   535.7 1038.07
   545.6 1041.76   565.6 1053.22   605.4 1070.58   625.3 1082.77   645.3 1088.08
   705.0 1082.63   754.8 1084.37   834.6 1106.95   844.5 1108.04   862.9 1115.08
#Mann= 3 , 0 , 0
       0     0.1       0   509.9   0.045       0   524.9     0.1       0
Bank Sta=   509.9,   524.9
Exp/Cntr=0.3,0.1

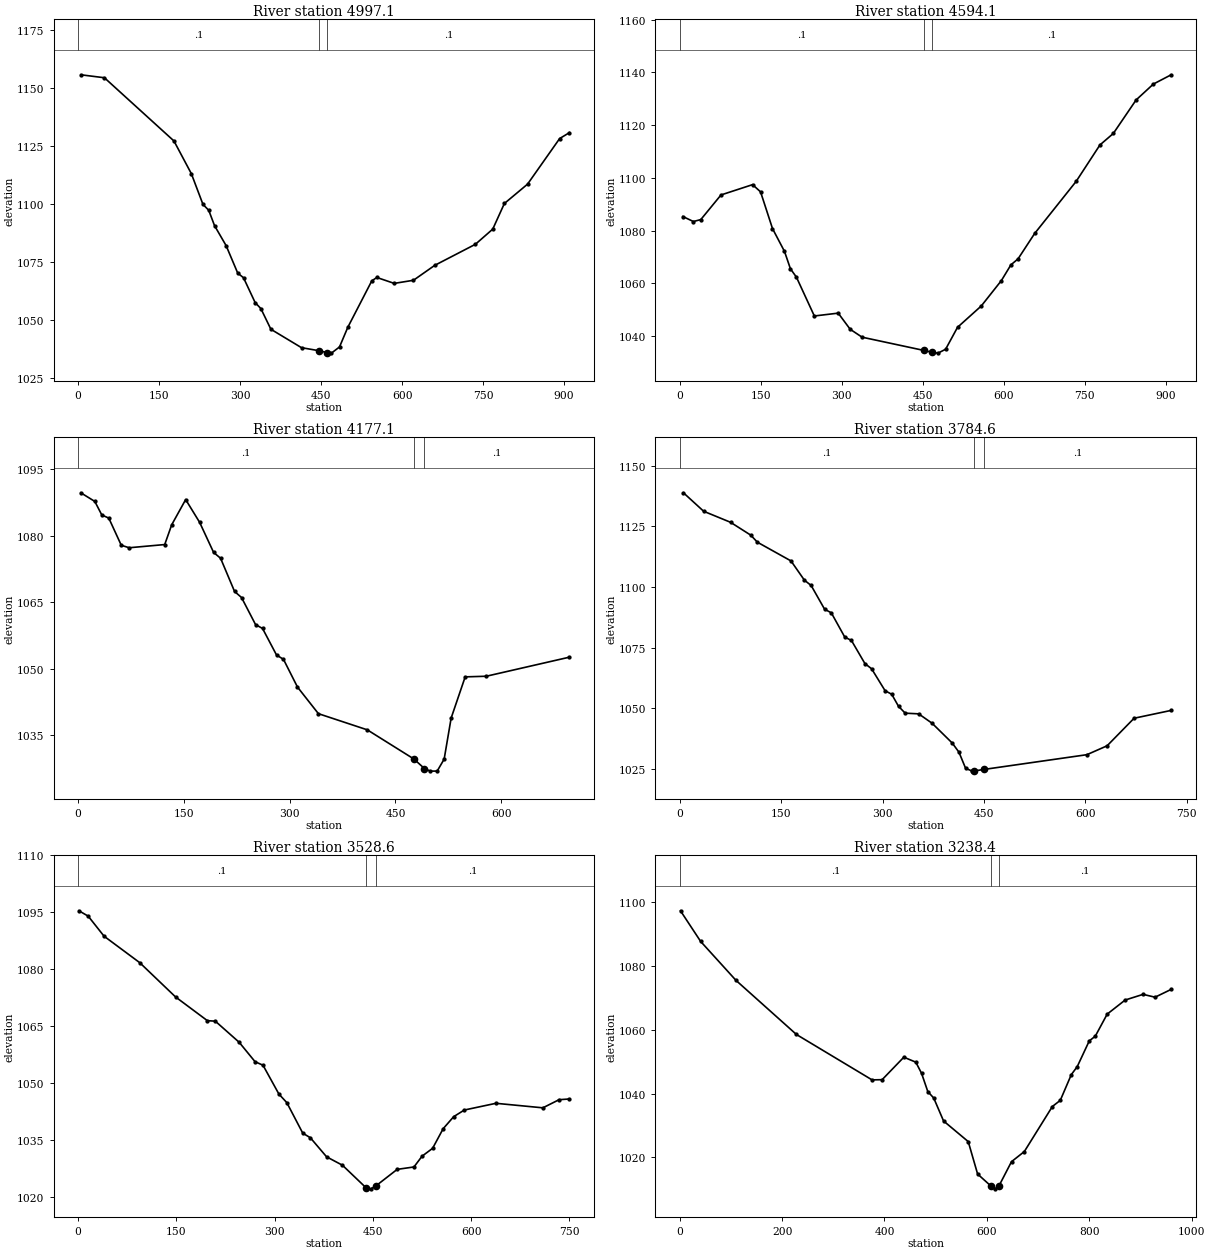
Type RM Length L Ch R = 1 ,4997.1,404.4,403,401.9
XS GIS Cut Line= 3
     1742946.356      375530.912     1742529.259      375712.723
     1742112.162      375894.535
#Sta/Elev= 30
     5.6 1155.83    48.7 1154.57   177.5 1127.29   209.7 1113.19   231.2 1099.94
   241.9 1097.39   252.6 1090.78   274.1 1082.14   295.6 1070.28   306.3 1068.29
   327.8 1057.59   338.5 1054.96   357.0 1046.06   413.7 1038.11   446.4 1036.79
   461.4 1035.95   469.1 1035.76   484.1 1038.43   499.5 1046.93   543.9 1066.95
   553.2 1068.40   585.4 1065.85   621.0 1067.19   660.5 1073.64   735.7 1082.71
   767.9 1089.27   789.4 1100.32   832.3 1108.66   891.8 1128.35   910.0 1130.90
#Mann= 3 , 0 , 0
       0     0.1       0   446.4   0.045       0   461.4     0.1       0
Bank Sta=   446.4,   461.4
Exp/Cntr=0.3,0.1

Type RM Length L Ch R = 1 ,4594.1,403.4,417,430.3
XS GIS Cut Line= 3
     1742769.236      375140.047     1742364.716      375348.161
     1741957.275      375551.225
#Sta/Elev= 30
     5.9 1085.31    25.4 1083.42    39.1 1084.16    76.5 1093.49   135.0 1097.40
   149.8 1094.66   171.9 1080.75   194.1 1072.10   205.1 1065.51   216.2 1062.34
   249.4 1047.61   293.6 1048.69   315.8 1042.57   337.9 1039.57   452.8 1034.53
   467.8 1033.82   478.5 1033.53   492.6 1035.01   514.6 1043.31   558.6 1051.40
   595.9 1061.04   613.5 1066.99   626.7 1069.25   657.5 1078.89   734.5 1098.67
   778.4 1112.44   803.2 1116.80   845.4 1129.50   877.4 1135.53   910.2 1139.03
#Mann= 3 , 0 , 0
       0     0.1       0   452.8   0.045       0   467.8     0.1       0
Bank Sta=   452.8,   467.8
Exp/Cntr=0.3,0.1

Type RM Length L Ch R = 1 ,4177.1,391.9,392.5,387.4
XS GIS Cut Line= 3
     1742738.339      375020.621     1742227.298      374961.787
     1742046.858      374935.654
#Sta/Elev= 30
     3.9 1089.65    23.7 1087.71    33.6 1084.66    43.5 1083.96    61.2 1077.84
    72.4 1077.28   122.8 1078.00   132.7 1082.45   152.5 1088.13   172.3 1083.00
   192.1 1076.23   202.0 1074.91   221.8 1067.44   231.7 1066.07   251.6 1059.97
   261.5 1059.10   281.3 1053.13   291.2 1052.14   311.0 1045.91   340.7 1039.91
   410.0 1036.27     476 1029.71     491 1027.56   499.2 1026.97   509.1 1026.98
   519.0 1029.68   528.9 1038.92   548.8 1048.20   578.7 1048.34   696.7 1052.64
#Mann= 3 , 0 , 0
       0     0.1       0     476   0.045       0     491     0.1       0
Bank Sta=     476,     491
Exp/Cntr=0.3,0.1

Type RM Length L Ch R = 1 ,3784.6,273.3,256,244.5
XS GIS Cut Line= 3
     1742818.733      374663.258     1742377.244      374601.451
     1742099.917      374645.871
#Sta/Elev= 30
     5.6 1138.79    35.4 1131.20    75.2 1126.65   105.0 1121.37   114.9 1118.45
   164.6 1110.73   184.4 1102.81   194.4 1100.61   214.3 1090.83   224.2 1089.36
   244.1 1079.36   254.0 1077.96   273.9 1068.45   283.8 1066.30   303.7 1057.28
   313.6 1055.78   323.6 1050.84   333.5 1048.01   353.4 1047.73   373.3 1043.85
   403.1 1035.69   413.0 1031.93   422.9 1025.24   432.9 1024.13     435 1024.18
     450 1024.83   602.2 1030.90   632.1 1034.57   672.0 1045.92   726.7 1049.14
#Mann= 3 , 0 , 0
       0     0.1       0     435   0.045       0     450     0.1       0
Bank Sta=     435,     450
Exp/Cntr=0.3,0.1

Type RM Length L Ch R = 1 ,3528.6,288.3,290.2,292
XS GIS Cut Line= 3
     1742638.670      374115.281     1742213.505      374422.007
     1742075.428      374600.975
#Sta/Elev= 30
     1.4 1095.37    15.4 1093.97    39.6 1088.70    94.1 1081.73   148.8 1072.71
   197.4 1066.47   209.5 1066.34   245.9 1060.79   270.2 1055.67   282.3 1054.75
   306.6 1047.16   318.7 1044.90   343.0 1036.88   354.6 1035.67   379.4 1030.65
   403.6 1028.44   440.0 1022.45   446.5 1022.15     455 1023.04   487.2 1027.35
   512.8 1027.98   525.2 1030.82   541.3 1032.89   557.4 1038.05   573.5 1041.22
   589.7 1042.96   638.0 1044.73   709.6 1043.54   734.4 1045.68   750.3 1045.87
#Mann= 3 , 0 , 0
       0     0.1       0     440   0.045       0     455     0.1       0
Bank Sta=     440,     455
Exp/Cntr=0.3,0.1

Type RM Length L Ch R = 1 ,3238.4,635.1,650.7,666.2
XS GIS Cut Line= 3
     1742647.448      374089.985     1742229.505      374077.015
     1741773.298      374368.961
#Sta/Elev= 30
     1.6 1097.38    40.9 1087.78   109.9 1075.56   228.0 1058.57   375.7 1044.32
   395.4 1044.38   437.8 1051.44   461.2 1049.88   472.4 1046.39   484.6 1040.66
   496.2 1038.62   515.4 1031.42   563.6 1024.95   581.9 1014.77   608.4 1010.93
   615.2 1010.03   623.4 1010.97   648.1 1018.64   673.2 1021.83   727.9 1035.96
   743.4 1037.90   764.9 1045.96   776.6 1048.51   800.0 1056.56   811.7 1058.02
   835.0 1064.96   870.1 1069.38   905.1 1071.16   928.5 1070.27   959.8 1072.71
#Mann= 3 , 0 , 0
       0     0.1       0   608.4   0.045       0   623.4     0.1       0
Bank Sta=   608.4,   623.4
Exp/Cntr=0.3,0.1

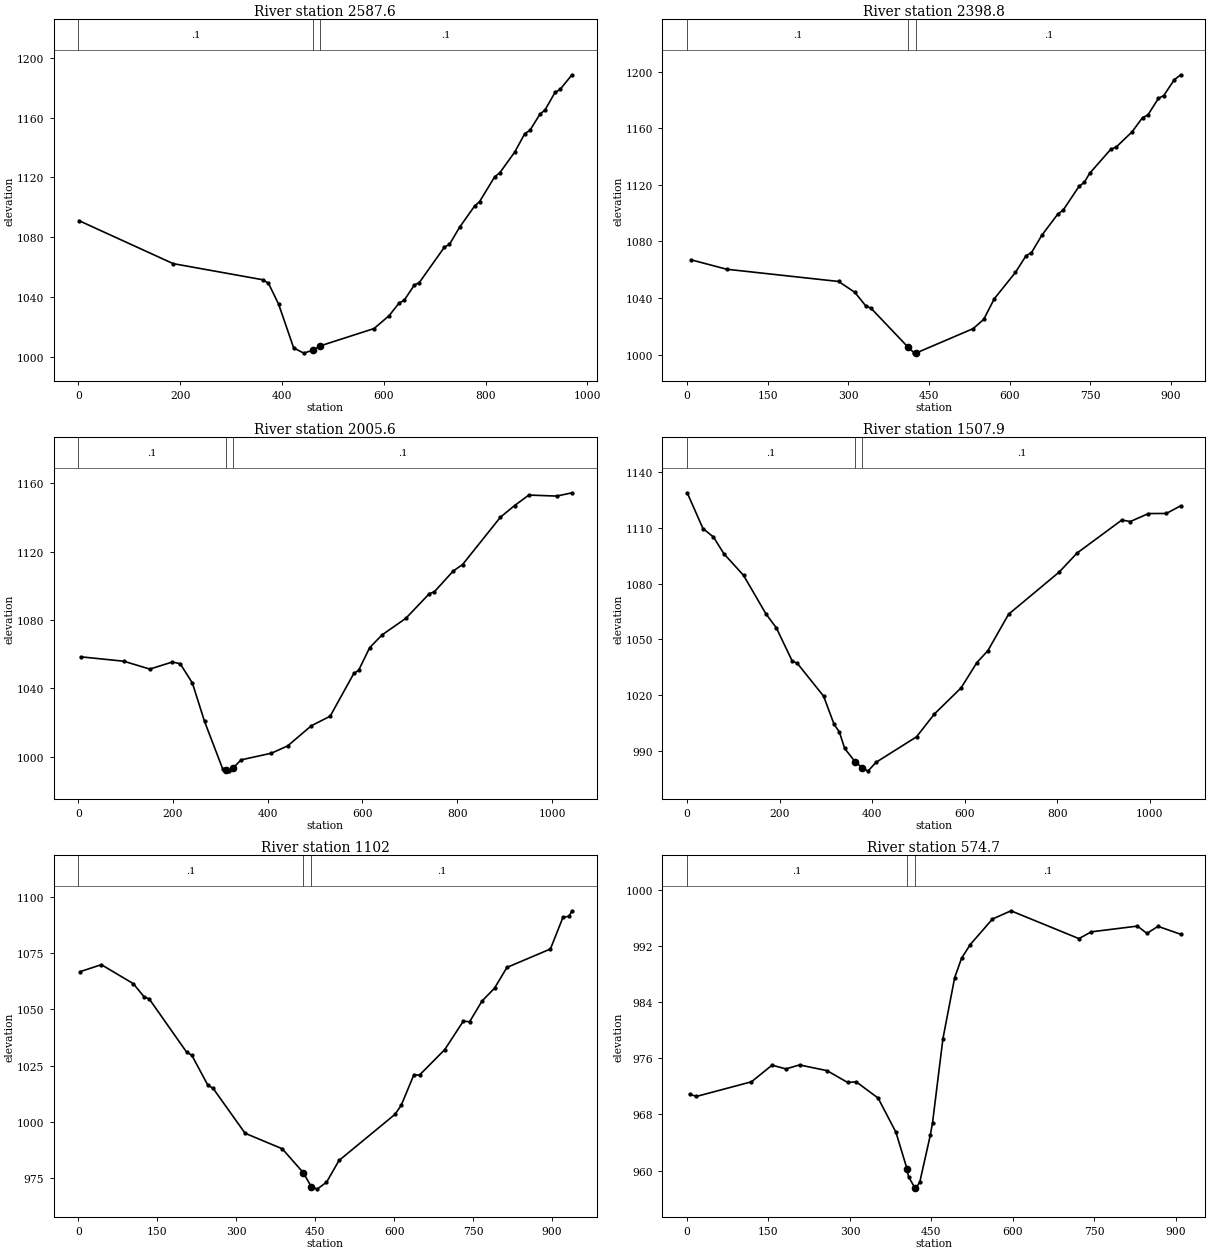
Type RM Length L Ch R = 1 ,2587.6,185.4,188.8,192.2
XS GIS Cut Line= 3
     1742633.906      373993.029     1742347.592      373763.633
     1741746.223      373716.183
#Sta/Elev= 30
     1.9 1090.95   186.4 1062.24   362.9 1051.41   373.6 1049.04   393.4 1035.17
   423.0 1005.84   442.7 1002.31   460.3 1004.18   475.3 1007.17   580.9 1018.77
   610.5 1027.40   630.3 1035.97   639.8 1037.58   659.9 1047.86   669.8 1049.59
   719.1 1073.28   729.0 1075.14   748.7 1086.52   778.3 1100.79   788.2 1103.81
   817.8 1120.43   827.7 1123.01   857.3 1137.04   877.0 1149.38   886.9 1151.45
   906.7 1162.36   916.5 1165.06   936.3 1176.90   946.1 1178.85   969.5 1188.67
#Mann= 3 , 0 , 0
       0     0.1       0   460.3   0.045       0   475.3     0.1       0
Bank Sta=   460.3,   475.3
Exp/Cntr=0.3,0.1

Type RM Length L Ch R = 1 ,2398.8,380.6,393.3,405.5
XS GIS Cut Line= 3
     1742675.555      373662.076     1742221.205      373564.951
     1741768.048      373553.450
#Sta/Elev= 30
     7.3 1067.06    73.6 1060.37   281.9 1051.70   312.1 1044.01   332.2 1034.50
   342.3 1032.71   410.7 1005.36   422.8 1001.04   425.7 1001.07   532.0 1018.37
   551.6 1024.89   571.3 1039.48   610.7 1058.17   630.4 1069.96   640.2 1071.96
   659.9 1084.52   689.4 1099.37   699.3 1102.15   728.8 1118.98   738.7 1121.82
   748.5 1128.16   787.9 1145.20   797.7 1146.67   827.3 1157.46   846.9 1167.58
   856.8 1169.41   876.5 1181.21   886.3 1183.15   906.0 1194.41   917.9 1197.84
#Mann= 3 , 0 , 0
       0     0.1       0   410.7   0.045       0   425.7     0.1       0
Bank Sta=   410.7,   425.7
Exp/Cntr=0.3,0.1

Type RM Length L Ch R = 1 ,2005.6,538.5,497.6,456.8
XS GIS Cut Line= 3
     1742741.968      373505.808     1742414.942      373231.730
     1741808.291      373335.278
#Sta/Elev= 30
     5.2 1058.47    96.0 1055.90   151.1 1051.30   198.8 1055.44   215.2 1054.43
   240.9 1043.17   266.6 1020.70   305.1  992.81   311.7  992.19   318.0  991.66
   326.7  993.43   343.6  998.23   407.8 1002.14   442.0 1006.40   491.9 1018.15
   531.8 1023.78   581.7 1048.76   591.7 1050.52   615.2 1063.85   641.6 1071.34
   691.5 1080.96   741.4 1095.47   751.4 1096.38   791.4 1108.59   811.3 1112.42
   891.2 1140.09   921.1 1146.89   951.1 1153.00  1010.0 1152.41  1042.1 1154.31
#Mann= 3 , 0 , 0
       0     0.1       0   311.7   0.045       0   326.7     0.1       0
Bank Sta=   311.7,   326.7
Exp/Cntr=0.3,0.1

Type RM Length L Ch R = 1 ,1507.9,412.6,406,402.5
XS GIS Cut Line= 3
     1742549.175      372560.924     1742339.954      372926.776
     1741784.794      373256.180
#Sta/Elev= 30
     0.5 1129.04    34.5 1109.78    57.2 1105.22    79.9 1096.16   122.3 1084.52
   170.5 1063.83   193.2 1056.19   227.2 1038.46   238.5 1037.09   295.2 1019.43
   317.9 1004.22   329.2 1000.16   340.8  991.23   363.6  983.98   378.6  980.88
   391.0  979.02   408.6  983.78   496.0  997.50   534.5 1009.78   592.4 1023.91
   626.4 1037.52   650.2 1043.95   695.0 1063.60   804.5 1086.36   843.1 1096.59
   939.5 1114.34   958.2 1113.58   997.3 1117.87  1035.9 1117.91  1067.0 1122.07
#Mann= 3 , 0 , 0
       0     0.1       0   363.6   0.045       0   378.6     0.1       0
Bank Sta=   363.6,   378.6
Exp/Cntr=0.3,0.1

Type RM Length L Ch R = 1 ,1102,517.1,527.2,534.2
XS GIS Cut Line= 3
     1742071.731      372361.054     1741969.511      372798.331
     1741699.286      373205.440
#Sta/Elev= 30
     3.6 1066.76    44.0 1069.85   104.7 1061.41   124.9 1055.63   135.0 1054.60
   205.7 1031.07   215.8 1029.60   246.1 1016.39   256.2 1014.94   316.9  995.01
   387.6  988.11   427.6  977.46   442.6  971.28   453.7  970.21   471.5  973.24
   495.3  982.93   601.6 1003.41   613.4 1007.44   637.0 1020.68   648.8 1020.99
   696.1 1032.16   731.5 1044.83   743.3 1044.50   766.9 1053.71   790.6 1059.40
   814.2 1068.63   896.8 1076.82   920.5 1090.81   932.3 1091.39   937.7 1093.76
#Mann= 3 , 0 , 0
       0     0.1       0   427.6   0.045       0   442.6     0.1       0
Bank Sta=   427.6,   442.6
Exp/Cntr=0.3,0.1

Type RM Length L Ch R = 1 ,574.7,609.5,574.7,540
XS GIS Cut Line= 3
     1741769.308      372242.839     1741482.692      372596.711
     1741255.225      372989.202
#Sta/Elev= 30
     4.7  970.90    17.3  970.58   118.7  972.67   156.6  975.05   182.0  974.51
   207.3  975.08   257.9  974.26   295.8  972.57   311.4  972.67   351.8  970.35
   384.6  965.48     405  960.25   407.8  959.13     420  957.45   420.8  957.34
   428.8  958.42   447.9  965.03   452.1  966.85   471.2  978.83   492.8  987.54
   505.5  990.32   521.6  992.28   562.4  995.92   596.5  997.09   721.6  993.12
   744.3  994.09   829.3  994.91   846.7  993.87   867.2  994.87   909.0  993.74
#Mann= 3 , 0 , 0
       0     0.1       0     405   0.045       0     420     0.1       0
Bank Sta=     405,     420
Exp/Cntr=0.3,0.1